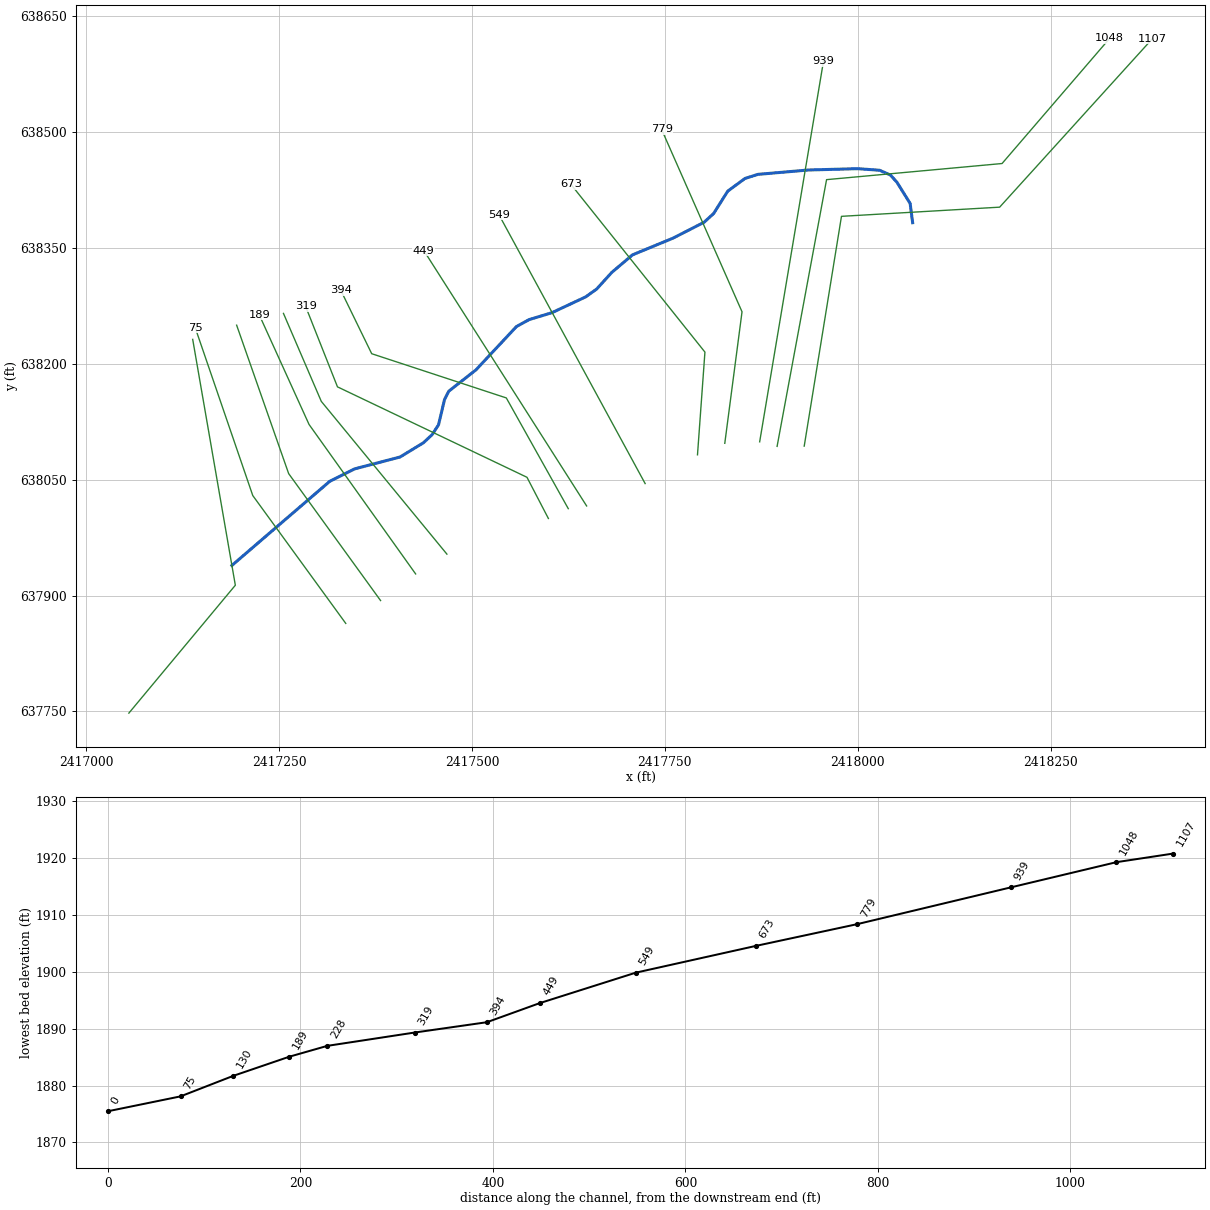
--- STRINGTRN_T1.prj (project) ---

Proj Title=STRINGTRN_T1
Current Plan=p01
Default Exp/Contr=0.3,0.1
English Units
Geom File=g01
Flow File=f01
Plan File=p01
Y Axis Title=Elevation
X Axis Title(PF)=Main Channel Distance
X Axis Title(XS)=Station
BEGIN DESCRIPTION:
Stream Name: Stringtown Run Tributary 1
Flood Zone: Approximate
Pendleton County, West Virginia
HEC-RAS Version: 5.0.7
Hydrology Method:
Regression equation
END DESCRIPTION:
DSS Export Rating Curves= 0
DSS Export Rating Curve Sorted= 0
DSS Export Volume Flow Curves= 0
DXF OffsetX= 0
DXF OffsetY= 0
DXF ScaleX= 1
DXF ScaleY= 10

--- STRINGTRN_T1.p01 (plan) ---

Plan Title=Floodplain
Program Version=5.07
Short Identifier=Floodplain
Geom File=g01
Flow File=f01
Subcritical Flow
K Sum by GR= 0
Std Step Tol= 0.01
Critical Tol= 0.01
Num of Std Step Trials= 20
Max Error Tol= 0.3
Flow Tol Ratio= 0.001
Split Flow NTrial= 30
Split Flow Tol= 0.02
Split Flow Ratio= 0.02
Log Output Level= 0
Friction Slope Method= 1
Unsteady Friction Slope Method= 2
Unsteady Bridges Friction Slope Method= 1
Parabolic Critical Depth
Global Vel Dist= 0 , 0 , 0
Global Log Level= 0
CheckData=True
Encroach Param=-1 ,0,0, 0
Computation Interval=1MIN
Output Interval=1HOUR
Instantaneous Interval=1HOUR
Mapping Interval=1HOUR
Computation Time Step Use Courant=        0
Computation Time Step Use Time Series=    0
Computation Time Step Count To Double=0
Computation Time Step Max Doubling=0
Computation Time Step Max Halving=0
Computation Time Step Residence Courant=0
Run HTab= 0
Run UNet= 0
Run Sediment= 0
Run PostProcess= 0
Run WQNet= 0
Run RASMapper= 0
UNET Theta= 1
UNET Theta Warmup= 1
UNET ZTol= 0.02
UNET ZSATol= 0.02
UNET MxIter= 20
UNET Max Iter WO Improvement= 0
UNET MaxInSteps= 0
UNET DtIC= 0
UNET DtMin= 0
UNET MaxCRTS= 20
UNET WFStab= 2
UNET SFStab= 1
UNET WFX= 1
UNET SFX= 1
UNET 1D Methodology=Finite Difference
UNET DSS MLevel= 4
UNET Pardiso=0
UNET DZMax Abort= 100
UNET Use Existing IB Tables=-1
UNET Froude Reduction=False
UNET Froude Limit= 0.8
UNET Froude Power= 4
UNET D1 Cores= 0
UNET D2 Coriolis=0
UNET D2 Cores= 0
UNET D2 Theta= 1
UNET D2 Theta Warmup= 1
UNET D2 Z Tol= 0.01
UNET D2 Volume Tol= 0.01
UNET D2 Max Iterations= 20
UNET D2 Equation= 0
UNET D2 RampUpFraction=0.1
UNET D2 TimeSlices= 1
UNET D2 BCVolumeCheck=0
UNET D1D2 MaxIter= 0
UNET D1D2 ZTol=0.01
UNET D1D2 QTol=0.1
UNET D1D2 MinQTol=1
Write IC File= 0
Write IC File at Fixed DateTime=0
Write IC File at Sim End=0
Echo Input=False
Echo Parameters=False
Echo Output=False
Write Detailed= 0
HDF Write Warmup=0
HDF Write Time Slices=0
HDF Flush=0
HDF Face Node Velocities=0
HDF Compression= 1
HDF Chunk Size= 1
HDF Spatial Parts= 1
HDF Use Max Rows=0
HDF Fixed Rows= 1
Calibration Method= 0
Calibration Iterations= 20
Calibration Max Change=0.05
Calibration Tolerance=0.2
Calibration Maximum=1.5
Calibration Minimum=0.5
Calibration Optimization Method= 1
WQ AD Non Conservative
WQ ULTIMATE=-1
WQ Max Comp Step=1HOUR
WQ Output Interval=15MIN
WQ Output Selected Increments= 0
WQ Output face flow=0
WQ Output face velocity=0
WQ Output face area=0
WQ Output face dispersion=0
WQ Output cell volume=0
WQ Output cell surface area=0
WQ Output cell continuity=0
WQ Output cumulative cell continuity=0
WQ Output face conc=0
WQ Output face dconc_dx=0
WQ Output face courant=0
WQ Output face peclet=0
WQ Output face adv mass=0
WQ Output face disp mass=0
WQ Output cell mass=0
WQ Output cell source sink temp=0
WQ Output nsm pathways=0
WQ Output nsm derived pathways=0
WQ Output MaxMinRange=-1
WQ Daily Max Min Mean=-1
WQ Daily Range=0
WQ Daily Time=0
WQ Create Restart=0
WQ Fixed Restart=0
WQ System Summary=0
WQ Write To DSS=0
WQ Use Fixed Temperature=0
Sorting and Armoring Iterations= 10
XS Update Threshold= 0.02
Bed Roughness Predictor= 0
Hydraulics Update Threshold= 0.02
Energy Slope Method= 1
Volume Change Method= 1
Sediment Retention Method= 0
XS Weighting Method= 0
Number of US Weighted Cross Sections= 1
Number of DS Weighted Cross Sections= 1
Upstream XS Weight=0
Main XS Weight=1
Downstream XS Weight=0
Number of DS XS's Weighted with US Boundary= 1
Upstream Boundary Weight= 1
Weight of XSs Associated with US Boundary= 0
Number of US XS's Weighted with DS Boundary= 1
Downstream Boundary Weight= 0.5
Weight of XSs Associated with DS Boundary= 0.5
Percentile Method= 0
Sediment Output Level= 3
Mass or Volume Output= 0
Output Increment Type= 1
Profile and TS Output Increment= 1
XS Output Flag= 0
XS Output Increment= 10
Write Gradation File= 0
Read Gradation Hotstart= 0
Write HDF5 File= 1
Write Binary Output= 1
Write DSS Sediment File= 0
SV Curve= 0
Specific Gage Flag= 0

--- STRINGTRN_T1.f01 (steady flow) ---

Flow Title=Flows
Program Version=5.07
Number of Profiles= 6
Profile Names=P100yr,P10yr,P25yr,P50yr,P500yr,P101yr
River Rch & RM=STRINGTRN_T1,Main            ,1107
     708     330     467     584    1040     862
Boundary for River Rch & Prof#=STRINGTRN_T1,Main            , 1
Up Type= 0
Dn Type= 1
Dn Known WS=1880.17
Boundary for River Rch & Prof#=STRINGTRN_T1,Main            , 2
Up Type= 0
Dn Type= 1
Dn Known WS=1878.6
Boundary for River Rch & Prof#=STRINGTRN_T1,Main            , 3
Up Type= 0
Dn Type= 1
Dn Known WS=1879.01
Boundary for River Rch & Prof#=STRINGTRN_T1,Main            , 4
Up Type= 0
Dn Type= 1
Dn Known WS=1879.81
Boundary for River Rch & Prof#=STRINGTRN_T1,Main            , 5
Up Type= 0
Dn Type= 1
Dn Known WS=1880.94
Boundary for River Rch & Prof#=STRINGTRN_T1,Main            , 6
Up Type= 0
Dn Type= 1
Dn Known WS=1880.54
DSS Import GetInterval= 0
DSS Import GetPeak= 0
DSS Import FillOption= 0

--- STRINGTRN_T1.g01 (geometry) ---

Geom Title=Geometry
Program Version=5.07

River Reach=STRINGTRN_T1    ,Main
Reach XY= 30
 2418071.0440145638382.5525485862418067.81722462638407.437333462
  2418050.725953638434.8867465172418042.26245925 638444.23890468
2418028.19481814638450.4380335882417999.82159959638452.485543441
 2417935.9319826638450.7631105452417870.67897504638445.131005882
2417853.86180403638439.8426216432417831.46326751638423.372685764
2417813.19001379638394.4301607362417800.81819932638383.114596994
 2417760.3970526638362.4736549732417708.14008231638340.960639961
2417681.23782625 638318.232616352417661.70903369638296.736001258
2417647.49860755638286.5748300852417603.82941402638266.129763847
2417574.03515756638257.0747512012417557.70484051638248.114610092
 2417505.2950298638192.0845143672417470.01998986638164.447026362
2417464.51541661638153.630249546 2417456.7622951638120.933026663
2417448.49642886638108.2496985622417437.26324012 638097.75932662
 2417406.8658673638079.2482939272417347.92735927 638063.87755238
2417315.92457479638047.8859567592417189.04535358 637938.93200679

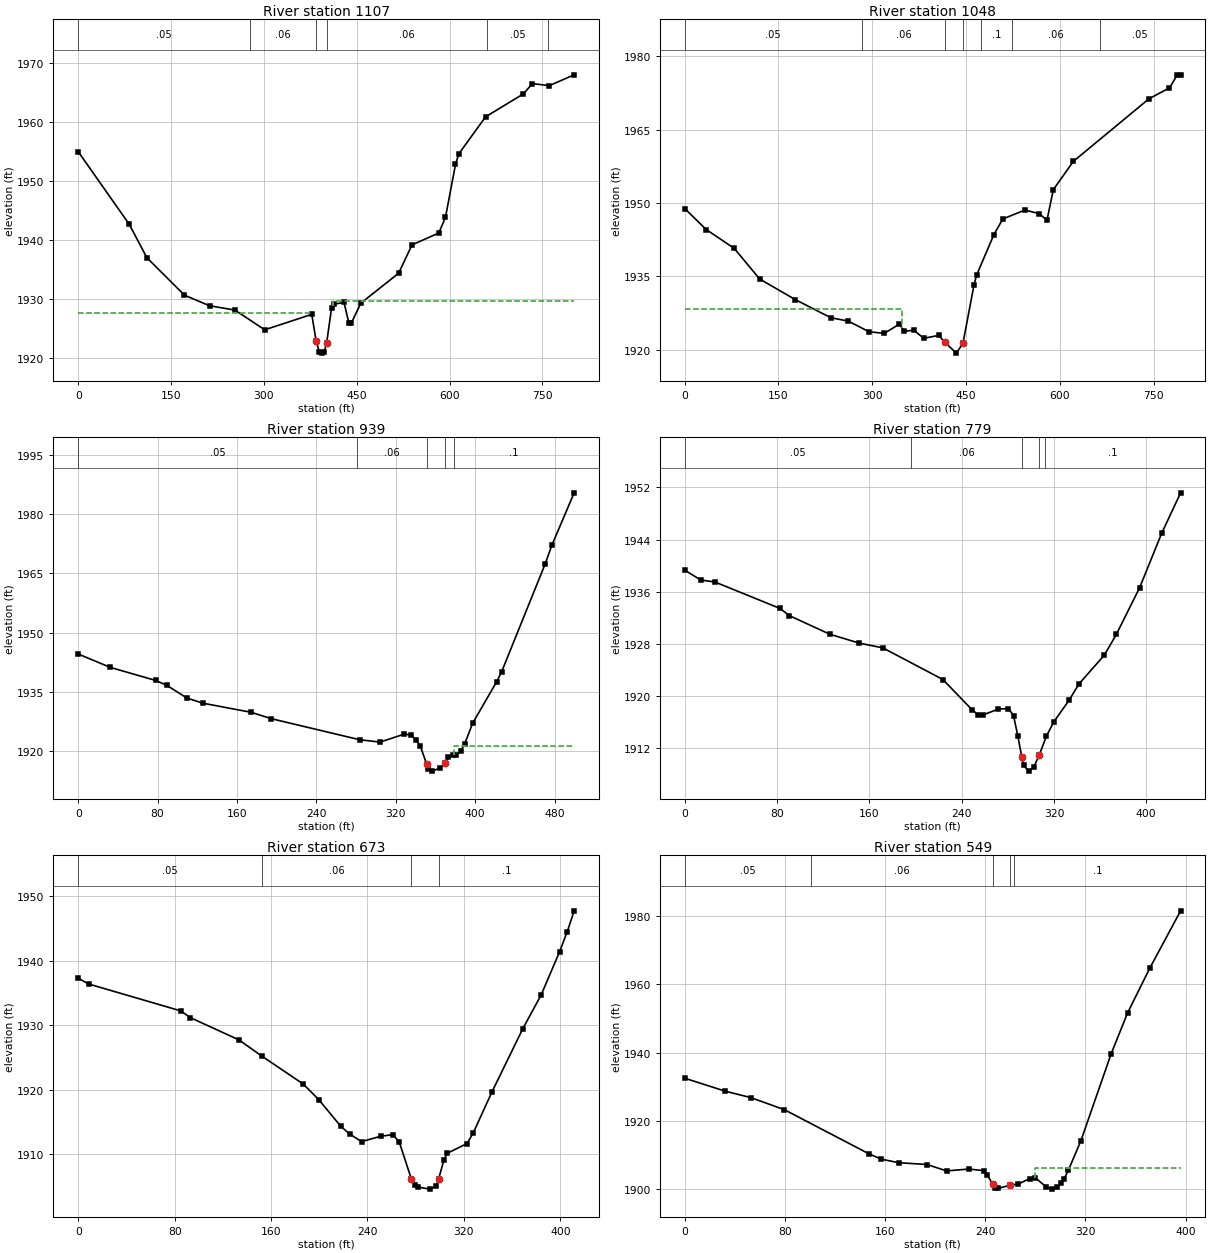
Type RM Length L Ch R = 1 ,1107    ,90,59.2,57
XS GIS Cut Line= 4
 2417930.5764799638093.3923180522417978.83700605638390.804216758
2418183.78268464  638402.6725344     2418381.775      638620.808
#Sta/Elev= 30
       0 1955.03    82.6 1942.67   110.9 1937.03   171.7 1930.66   212.2 1928.87
   253.1 1928.14   301.3 1924.79   377.3 1927.41   384.41922.868   389.4 1921.09
   393.4 1920.83   397.4 1921.05   401.4 1922.59   409.4 1928.57   413.4 1929.15
   429.4 1929.43   437.4  1925.9   441.2 1925.93   456.6 1929.31   517.7  1934.4
   539.3 1939.21   582.5 1941.22   593.3 1943.87   609.5 1952.85   614.9 1954.66
   658.1 1960.94   719.3 1964.84   733.8 1966.59     761 1966.23   801.2 1968.07
#Mann= 6 ,-1 , 0
       0     .05       0  277.62     .06       0   384.4    .045       0
   401.4     .06       0  660.13     .05       0  759.55     .06       0
#XS Ineff= 2 , 0
          374.22  1927.6  411.01          1929.7
Permanent Ineff=
       F       F
Bank Sta=384.4,401.4
XS Rating Curve= 0 ,0
Exp/Cntr(USF)=0,0
Exp/Cntr=0.5,0.3

Type RM Length L Ch R = 1 ,1048    ,59.6,109.3,130
XS GIS Cut Line= 4
2417895.42666033638093.0462725982417959.52321179638438.297042924
2418186.90059837638459.1575749232418326.37457415 638621.21075377
#Sta/Elev= 30
       0  1948.9    34.4  1944.6    79.2 1940.75   119.9 1934.48   176.8 1930.27
   233.8 1926.55   261.8 1925.86   294.8 1923.69   319.2 1923.35   343.6 1925.26
   351.2 1923.78   366.4    1924   382.5 1922.34   406.6 1922.95     416 1921.53
   434.7 1919.31   445.2 1921.36   462.8 1933.27   466.9 1935.25   494.5 1943.53
   508.8 1946.75   544.2 1948.59   567.3 1947.84   579.5 1946.48   589.7 1952.76
   621.7 1958.54   742.7 1971.35   775.5 1973.58   787.7 1976.17   793.3 1976.25
#Mann= 7 ,-1 , 0
       0     .05       0  283.47     .06       0     416    .045       0
   445.2     .06       0  474.05      .1       0  522.86     .06       0
  664.15     .05       0
#XS Ineff= 2 , 0
          347.55  1928.3
Permanent Ineff=
       F       F
Bank Sta=416,445.2
XS Rating Curve= 0 ,0
Exp/Cntr(USF)=0,0
Exp/Cntr=0.5,0.3

Type RM Length L Ch R = 1 ,939     ,155.2,160.1,169.6
XS GIS Cut Line= 2
2417872.84486443638098.9345597112417955.57834516638591.824074621
#Sta/Elev= 30
       0 1944.56    32.4 1941.17      78 1937.87    89.2 1936.64   109.5 1933.42
   125.7  1932.1   174.4 1929.79   194.6 1928.18   283.9 1922.83   304.2 1922.25
   328.5 1924.26     335 1924.06   340.7 1922.76   344.7 1921.27   351.31916.597
   352.8 1915.49   356.9 1914.89     365 1915.73   369.8  1916.9   373.1 1918.38
   377.2 1919.04   381.2 1919.06   385.3 1919.91   389.3 1921.68   397.5 1927.02
   421.8 1937.59   426.6 1939.99   470.5 1967.33   477.4 1972.17   499.8 1985.41
#Mann= 5 ,-1 , 0
       0     .05       0  281.02     .06       0   351.3    .045       0
   369.8     .06       0  378.56      .1       0
#XS Ineff= 2 , 0
                          378.54         1921.15
Permanent Ineff=
       F       F
Bank Sta=351.3,369.8
XS Rating Curve= 0 ,0
Exp/Cntr(USF)=0,0
Exp/Cntr=0.5,0.3

Type RM Length L Ch R = 1 ,779     ,100.3,105.6,109.5
XS GIS Cut Line= 3
2417827.65259203638097.0146255232417849.99189796638267.218861182
2417745.74180361 638503.37723816
#Sta/Elev= 30
       0  1939.3      14 1937.77    26.1 1937.48    82.6 1933.41    90.6 1932.31
   125.7 1929.45   151.2 1928.08   171.7 1927.35   223.8 1922.48     249 1917.84
   254.4 1917.06   258.8 1917.06   271.9 1917.94   280.6 1918.02     285 1916.94
   288.7 1913.81   292.2 1910.54   293.7 1909.29   298.1  1908.4   302.5 1909.01
   307.3 1910.87   313.4 1913.75     320    1916   333.1 1919.29   341.8 1921.82
   363.7 1926.23   374.1 1929.42   394.3 1936.61   413.5 1945.01   429.8 1951.18
#Mann= 5 ,-1 , 0
       0     .05       0  196.23     .06       0   292.2    .045       0
   307.3     .06       0  312.07      .1       0
Bank Sta=292.2,307.3
XS Rating Curve= 0 ,0
Exp/Cntr(USF)=0,0
Exp/Cntr=0.3,0.1

Type RM Length L Ch R = 1 ,673     ,127.7,124.5,121.9
XS GIS Cut Line= 3
2417792.28999032638082.0971172892417801.92821213638215.079800754
2417628.20639586 638432.30852702
#Sta/Elev= 30
       0 1937.27     8.8 1936.38      85 1932.22      93 1931.17   133.3 1927.72
   152.5 1925.18   186.7 1920.87   199.7 1918.42     218 1914.28   225.3  1913.1
   235.1 1911.93   250.9 1912.76   261.1 1913.01   266.3 1911.91   276.5  1906.1
   279.3 1905.23   281.6 1904.88     292 1904.56     297 1905.03   299.1  1906.2
   303.4 1909.04   306.2 1910.12   322.6 1911.63   327.7 1913.26   343.2  1919.6
   368.8 1929.42   384.1 1934.68   399.4 1941.39   405.8 1944.52   411.5 1947.74
#Mann= 4 ,-1 , 0
       0     .05       0   152.5     .06       0   276.5    .045       0
   299.1      .1       0
Bank Sta=276.5,299.1
XS Rating Curve= 0 ,0
Exp/Cntr(USF)=0,0
Exp/Cntr=0.3,0.1

Type RM Length L Ch R = 1 ,549     ,98.8,99.8,100.4
XS GIS Cut Line= 2
2417724.46627416638044.8895783522417535.11406199638392.744484981
#Sta/Elev= 30
       0 1932.45    32.2 1928.66    52.9 1926.74    79.7 1923.19   147.2 1910.23
   157.1 1908.66   170.8 1907.63   193.6 1907.09   209.2 1905.21   226.9 1905.76
   238.7  1905.3   241.6 1904.02   246.2 1901.24   248.2 1900.19   250.5 1900.08
   260.21901.055   266.4 1901.33   275.5 1902.95   279.9 1903.23   288.8 1900.49
   293.7 1899.86   297.6 1900.34   300.6 1901.52   302.9 1902.75   306.5 1905.45
   316.5 1914.12   340.5  1939.5   353.7 1951.61   371.7 1964.95   396.1 1981.63
#Mann= 5 ,-1 , 0
       0     .05       0  101.11     .06       0   246.2    .045       0
   260.2     .06       0  263.26      .1       0
#XS Ineff= 2 , 0
                          279.47          1906.2
Permanent Ineff=
       F       F
Bank Sta=246.2,260.2
XS Rating Curve= 0 ,0
Exp/Cntr(USF)=0,0
Exp/Cntr=0.3,0.1

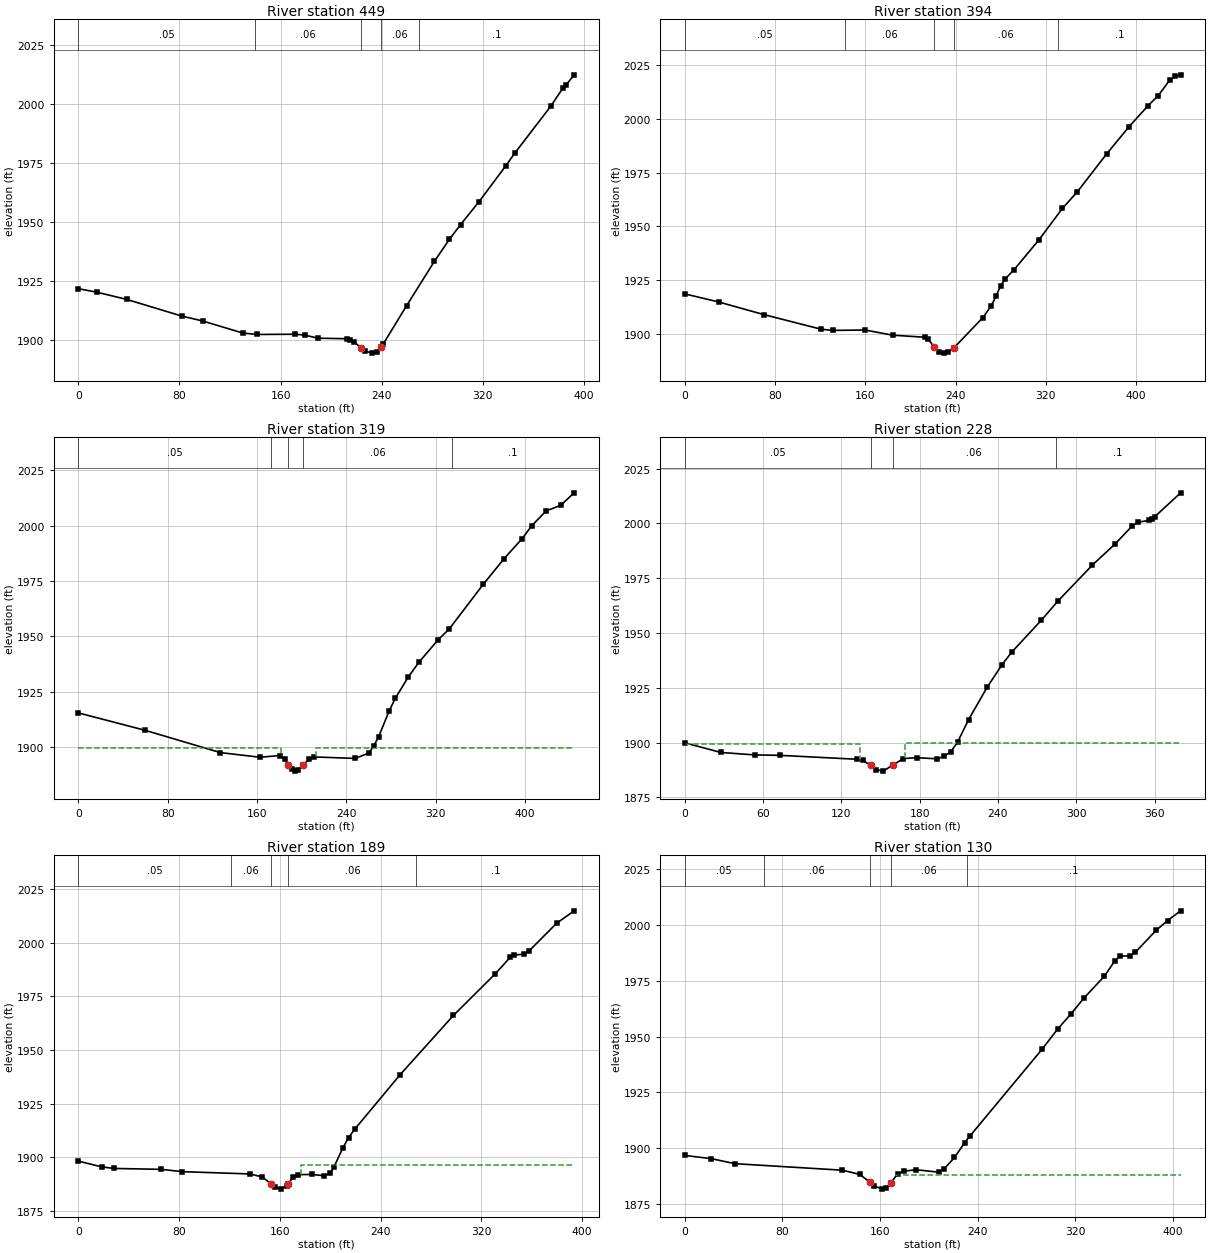
Type RM Length L Ch R = 1 ,449     ,44.9,54.9,64.2
XS GIS Cut Line= 2
2417648.63800974638015.9383600772417437.69110032638346.543275189
#Sta/Elev= 30
       0  1921.8    15.1 1920.26    38.3 1917.25    81.7 1910.22    98.4 1908.11
   129.9 1903.04   141.1 1902.41   171.5  1902.5   179.1 1902.15   189.4 1900.83
   212.3  1900.6     215  1900.2   217.9 1899.41   223.7 1896.67   226.6 1895.39
   232.3  1894.5     236 1895.18   239.51897.223     241 1898.21   259.7 1914.64
   281.6 1933.35   293.5 1942.71   302.4 1948.99   316.7 1958.48   338.2 1973.92
   345.1 1979.13   373.6 1999.03   383.1 2006.62   385.9 2008.18   392.2  2012.4
#Mann= 5 ,-1 , 0
       0     .05       0   139.7     .06       0   223.7    .045       0
   239.5     .06       0  269.68      .1       0
Bank Sta=223.7,239.5
XS Rating Curve= 0 ,0
Exp/Cntr(USF)=0,0
Exp/Cntr=0.5,0.3

Type RM Length L Ch R = 1 ,394     ,77.8,75.2,72.6
XS GIS Cut Line= 4
2417624.87933007638012.4184333612417544.59511737638155.737571175
2417370.17503211638212.9831376172417330.02603943638295.312648066
#Sta/Elev= 30
       0 1918.64    30.3 1914.85    69.8 1909.07   120.9 1902.23   131.2  1901.7
   159.9 1901.87   184.1 1899.47   212.6 1898.52   215.8 1897.57   220.91894.052
   225.3 1891.78   229.4 1891.14   233.6 1891.59   238.5 1893.58   264.2 1907.68
   271.5 1913.05   275.7 1917.48   279.9 1922.46   284.1 1925.67   291.9 1929.95
   313.6 1943.58   334.6 1958.31   347.8    1966   373.9 1983.69   393.7 1996.29
   410.4 2005.96   419.6 2010.72   429.6  2017.8   434.5 2019.68   439.4 2020.36
#Mann= 5 ,-1 , 0
       0     .05       0  142.26     .06       0   220.9    .045       0
   238.5     .06       0  330.89      .1       0
#XS Ineff= 2 , 0
          215.54  1897.5  246.16          1896.7
Permanent Ineff=
       F       F
Bank Sta=220.9,238.5
XS Rating Curve= 0 ,0
Exp/Cntr(USF)=0,0
Exp/Cntr=0.5,0.3

Type RM Length L Ch R = 1 ,319     ,94.5,90.6,85.6
XS GIS Cut Line= 4
2417599.09100933637999.7238841472417571.35231525638053.031466566
2417325.82526127638170.0971900342417284.59413805638274.130218653
#Sta/Elev= 30
       0 1915.56    60.1 1907.67   127.2 1897.66   162.7 1895.58   180.4 1896.35
     185 1894.93   187.91892.223     191 1890.16   193.7 1889.32     197 1889.99
   201.4 1892.22     207 1894.92   211.4 1895.71     248 1895.05   260.2 1897.48
   264.6 1900.79   268.9 1904.75   278.2  1916.3     284 1922.28   295.6 1931.84
     305  1938.4   322.2  1948.5   332.1 1953.36   362.8 1973.63   381.3 1985.08
   397.5 1994.14   406.1 1999.95     419 2006.61   431.9 2009.09     444 2014.73
#Mann= 5 ,-1 , 0
       0     .05       0  172.73     .06       0   187.9    .045       0
   201.4     .06       0   334.5      .1       0
#XS Ineff= 2 , 0
          181.12 1899.76  212.97         1899.69
Permanent Ineff=
       F       F
Bank Sta=187.9,201.4
XS Rating Curve= 0 ,0
Exp/Cntr(USF)=0,0
Exp/Cntr=0.5,0.3

Type RM Length L Ch R = 1 ,228     ,41.1,39.5,38
XS GIS Cut Line= 3
2417467.61968009637953.5649295242417304.87930789638151.265261297
2417255.86533137638265.139848637
#Sta/Elev= 30
       0  1899.9    27.6  1895.5    53.5 1894.38    72.6 1894.19   132.3 1892.38
   136.4 1891.95   142.41889.581   146.8 1887.66     152 1886.98   159.21889.645
   167.5 1892.71   177.9 1893.12   193.4 1892.59   198.6 1893.67   203.8 1895.83
     209 1900.14   217.5 1910.48   231.7 1925.23   243.1 1935.52   250.4 1941.16
   273.1 1955.73   286.1 1964.66   312.4 1981.01   329.7 1990.58   342.8 1998.79
   347.1 2000.48   355.8 2001.43   357.9 2002.11   360.2 2003.07     380 2013.95
#Mann= 4 ,-1 , 0
       0     .05       0   142.4    .045       0   159.2     .06       0
  284.28      .1       0
#XS Ineff= 2 , 0
          134.57 1899.43  168.92         1899.96
Permanent Ineff=
       F       F
Bank Sta=142.4,159.2
XS Rating Curve= 0 ,0
Exp/Cntr(USF)=0,0
Exp/Cntr=0.3,0.1

Type RM Length L Ch R = 1 ,189     ,58.4,58.4,58.5
XS GIS Cut Line= 3
2417427.09991218637927.9264646682417288.99220053638121.428520093
2417224.38888956638263.531706218
#Sta/Elev= 30
       0 1898.15    18.4 1895.46    28.2 1894.72    65.5  1894.3    82.7 1893.22
   136.3 1892.15   146.2 1890.72   153.21887.488     156 1885.97   160.9 1885.07
   165.7 1886.76   166.81887.606   170.7 1890.65   174.4  1891.8   185.5 1891.93
   195.3  1891.3   200.2 1892.55   203.1  1895.5     210 1904.15   214.6 1909.13
   219.9 1913.28   255.6 1938.47   297.9 1966.08   331.2 1985.53   343.2  1993.3
   346.3 1994.27   353.6 1994.65     358 1996.19   379.9 2009.09   393.8 2014.88
#Mann= 5 ,-1 , 0
       0     .05       0  120.88     .06       0   153.2    .045       0
   166.8     .06       0  268.56      .1       0
#XS Ineff= 2 , 0
                          177.01         1896.22
Permanent Ineff=
       F       F
Bank Sta=153.2,166.8
XS Rating Curve= 0 ,0
Exp/Cntr(USF)=0,0
Exp/Cntr=0.3,0.1

Type RM Length L Ch R = 1 ,130     ,54.9,54.6,54.4
XS GIS Cut Line= 3
2417381.67105775637893.4660200872417262.57354288638057.800177868
2417195.19424358638249.910757906
#Sta/Elev= 30
       0 1896.77    21.5 1895.36    41.3 1893.08   129.1 1890.17   143.5 1888.28
     1521884.665   154.9 1883.24   161.8 1881.69   164.8 1882.01     1691884.558
   174.7 1888.69   179.6 1889.73   189.5 1890.37   208.3 1889.28   212.6 1890.71
   221.1 1895.86   229.5 1902.55   233.8  1905.5   293.1 1944.47   305.8 1953.48
   316.7 1960.21     327 1967.13     344 1977.07   352.5 1983.91   356.7 1985.98
   365.2 1986.28   369.4 1987.79   386.4 1997.61   395.8 2001.99   406.5 2006.35
#Mann= 5 ,-1 , 0
       0     .05       0   64.53     .06       0     152    .045       0
     169     .06       0  231.55      .1       0
#XS Ineff= 2 , 0
           144.2  1887.4  173.35          1888.2
Permanent Ineff=
       F       F
Bank Sta=152,169
XS Rating Curve= 0 ,0
Exp/Cntr(USF)=0,0
Exp/Cntr=0.5,0.3

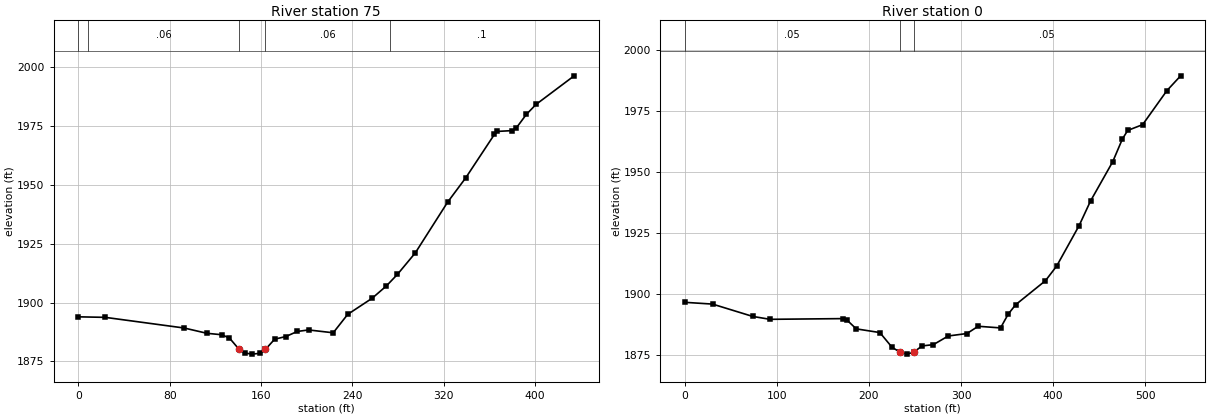
Type RM Length L Ch R = 1 ,75      ,75.5,75.5,75.5
XS GIS Cut Line= 3
2417336.55624656637863.8914637372417216.07480765638029.396346465
2417141.55928821638246.496779847
#Sta/Elev= 30
       0 1893.94    23.5 1893.72    92.8 1889.18   112.6 1886.94   125.4 1886.34
   132.3 1884.95   140.81880.112   145.8 1878.56   152.3 1878.09   159.4 1878.46
   163.8 1880.08   171.9 1884.43   181.8 1885.58   191.7 1887.72   201.6 1888.37
   223.2 1887.16   235.9 1894.99   257.3 1901.84   269.7 1907.04   279.4 1911.96
   295.1 1921.12   323.4 1942.68   339.2 1952.97   364.4 1971.49     367 1972.74
   379.7 1973.07   383.2 1973.99   392.4    1980   400.8  1984.2   434.2 1996.36
#Mann= 5 ,-1 , 0
       0     .05       0    8.36     .06       0   140.8    .045       0
   163.8     .06       0  273.01      .1       0
Bank Sta=140.8,163.8
XS Rating Curve= 0 ,0
Exp/Cntr(USF)=0,0
Exp/Cntr=0.5,0.3

Type RM Length L Ch R = 1 ,0       ,,,
XS GIS Cut Line= 3
2417055.54844224 637747.776691162417193.49605069 637913.29215886
2417138.25553422 638231.52510979
#Sta/Elev= 30
       0 1896.69    30.1 1895.97    73.7 1890.92    92.5 1889.73     172 1890.02
   175.9 1889.49   186.2 1885.82   211.8 1884.31   225.2 1878.21   233.3 1876.42
   241.4 1875.47   248.4 1876.23   257.7 1878.83   269.9 1879.35   286.1  1882.9
   306.4 1883.91   318.6 1886.88   342.9 1886.21   351.1 1891.78   359.2 1895.68
   391.7 1905.57   403.8 1911.52   428.2 1928.11   440.6 1938.19   464.7 1954.28
   475.2 1963.59     481 1967.11   497.2 1969.48   523.6 1983.44538.4562 1989.48
#Mann= 3 ,-1 , 0
       0     .05       0   233.3    .045       0   248.4     .05       0
Bank Sta=233.3,248.4
XS Rating Curve= 0 ,0
Exp/Cntr(USF)=0,0
Exp/Cntr=0.3,0.1
LCMann Table=0

Chan Stop Cuts=-1
Use User Specified Reach Order=0
Composite Channel Slope=5